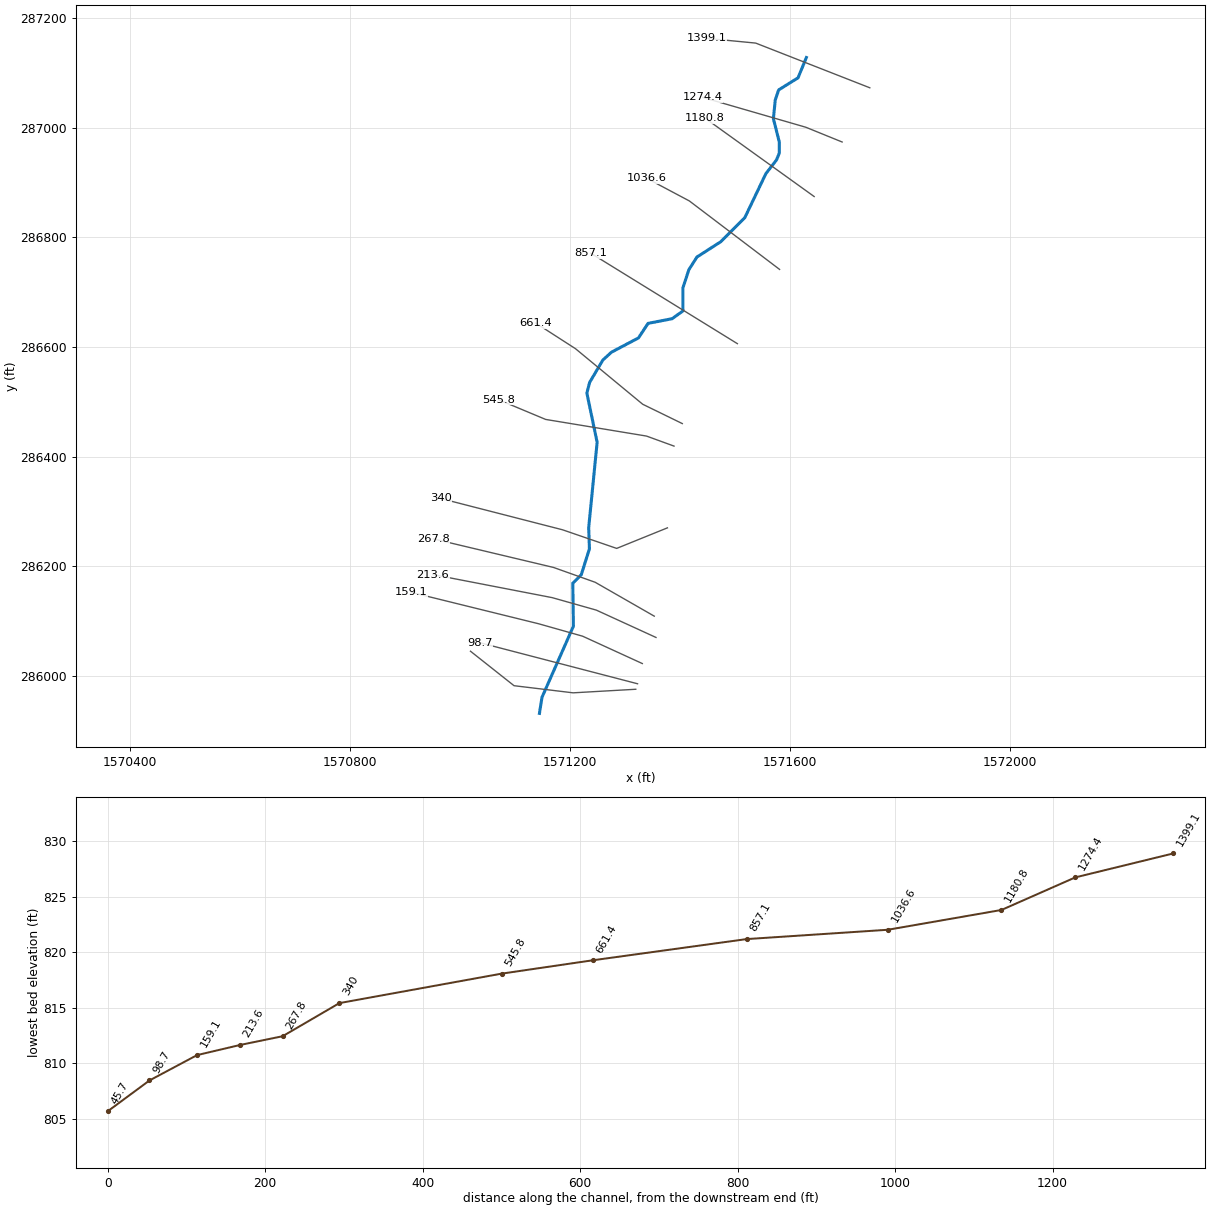
--- YEAGERRN.prj (project) ---

Proj Title=YEAGERRN
Current Plan=p01
Default Exp/Contr=0,0
English Units
Geom File=g01
Flow File=f01
Plan File=p01
BEGIN DESCRIPTION:
END DESCRIPTION:
DSS Export Rating Curves= 0
DSS Export Rating Curve Sorted= 0
DSS Export Volume Flow Curves= 0
DXF OffsetX= 0
DXF OffsetY= 0
DXF ScaleX= 0
DXF ScaleY= 0

--- YEAGERRN.p01 (plan) ---

Plan Title=Floodplain
Program Version=4.00
Geom File=g01
Flow File=f01
K Sum by GR=0
Std Step Tol=0.01
Critical Tol=0.01
Num of Std Step Trials=20
Max Error Tol=0.3
Flow Tol Ratio=0.001
Split Flow NTrial=30
Split Flow Tol=0.02
Split Flow Ratio=0.02
Log Output Level=0
Friction Slope Method=1
Unsteady Friction Slope Method=2
Unsteady Bridges Friction Slope Method=1
Global Log Level=0
CheckData=False
Run HTab=0
Run UNet=0
Run PostProcess=0
UNET Theta=0
UNET Theta Warmup=0
UNET ZTol=0
UNET ZSATol=0
UNET MxIter=0
UNET MaxInSteps=0
UNET DtIC=0
UNET DtMin=0
UNET MaxCRTS=0
UNET WFStab=0
UNET SFStab=0
UNET WFX=0
UNET SFX=0
UNET DSS MLevel=0
UNET DZMax Abort=0
UNET Convert EG Bridges=0
UNET Use Existing IB Tables=0
UNET Froude Limit=0
UNET Froude Power=0
Write IC File=0
Echo Input=False
Echo Output=False
Write Detailed=0

--- YEAGERRN.f01 (steady flow) ---

Flow Title=NFF Regression Equation
Program Version=4.10
Number of Profiles= 1
Profile Names=P100yr
River Rch & RM=YEAGERRN,Main            ,1399.1
408.8576
River Rch & RM=YEAGERRN,Main            ,857.1
415.3471
River Rch & RM=YEAGERRN,Main            ,545.8
421.9371
Boundary for River Rch & Prof#=YEAGERRN,Main            , 1
Up Type= 0
Dn Type= 3
Dn Slope=0.0524
DSS Import GetInterval= 0
DSS Import GetPeak= 0
DSS Import FillOption= 0

--- YEAGERRN.g01 (geometry) ---

Geom Title=USGS 10m DEM
Program Version=4.10

River Reach=YEAGERRN        ,Main
Reach XY= 30
     1571630.346      287128.384     1571615.157      287091.256
     1571579.985      287069.323     1571573.758      287050.641
     1571570.362      287016.675     1571581.118      286974.216
     1571581.118      286953.836     1571576.023      286941.382
     1571556.775      286916.473     1571518.279      286835.859
     1571474.406      286791.929     1571431.381      286764.189
     1571416.662      286740.979     1571405.906      286708.144
     1571405.906      286665.686     1571386.093      286651.533
     1571342.502      286643.042     1571324.953      286616.434
     1571275.814      286590.393     1571260.279      286576.075
      1571236.19      286535.276     1571231.199      286515.745
     1571249.862      286425.901     1571234.488      286269.975
     1571235.861       286231.56     1571221.017      286184.164
     1571205.617      286168.641     1571206.694      286090.154
     1571149.571      285960.312     1571144.981      285931.043

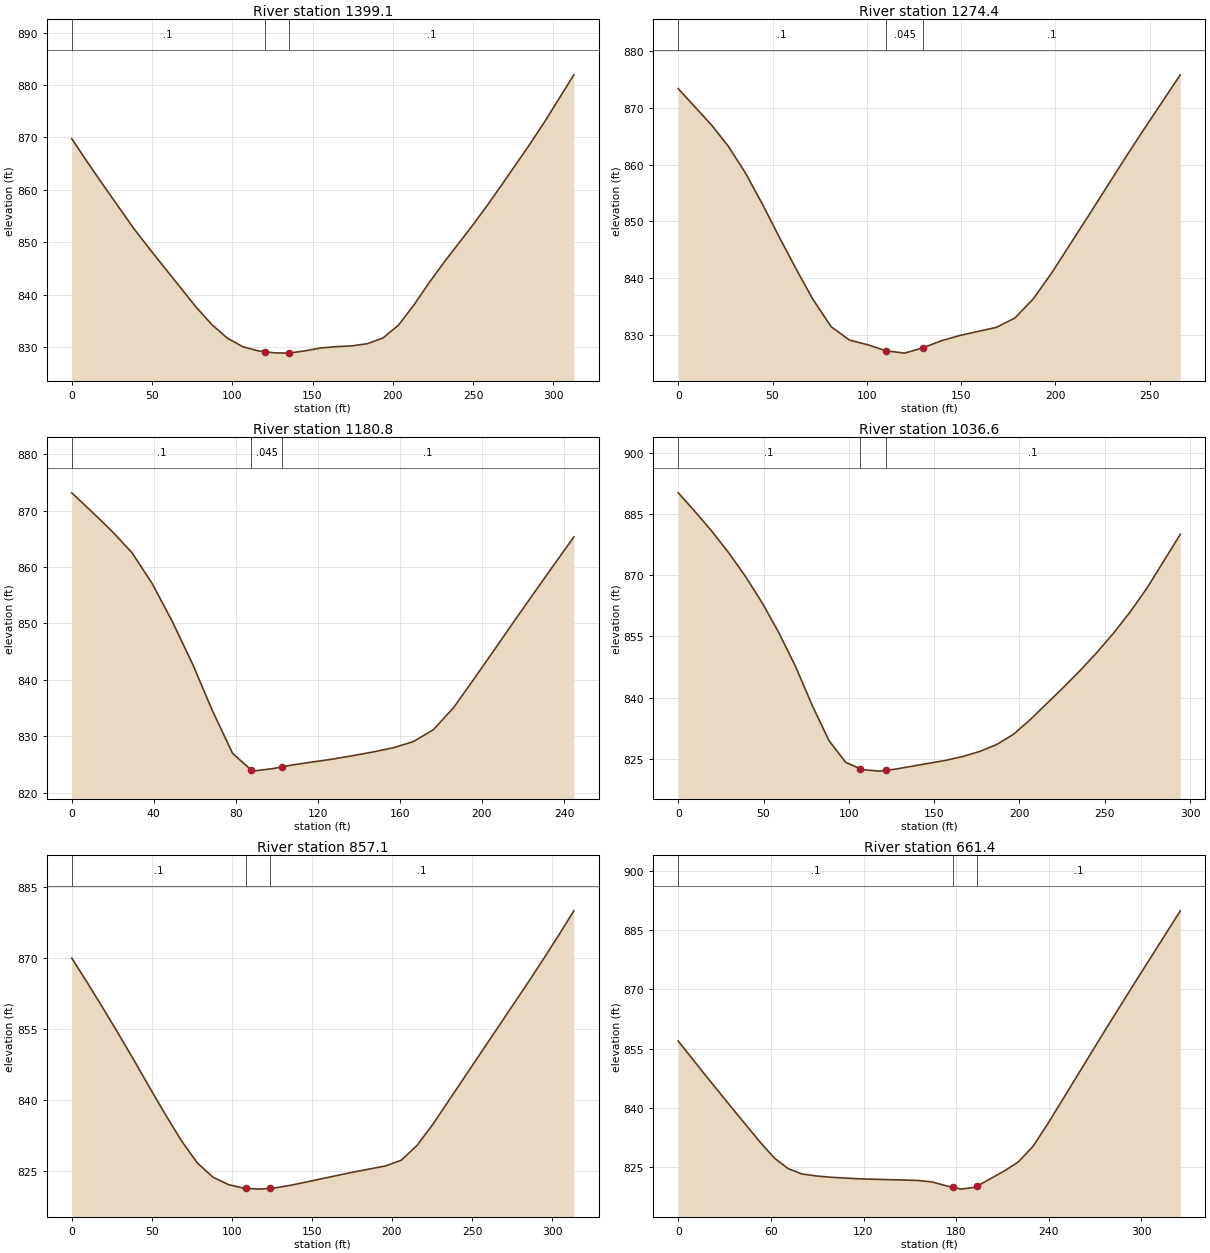
Type RM Length L Ch R = 1 ,1399.1  ,123.8,124.7,127
XS GIS Cut Line= 3
     1571745.685      287073.154     1571538.219      287154.751
      1571448.81      287163.432
#Sta/Elev= 29
       0  869.77     9.7  865.32    19.4  861.01    38.8  852.58    48.5  848.75
    77.5  837.65    87.2  834.36    96.9  831.75   106.6  830.11   116.3  829.31
   120.2  829.17     126  828.95   135.2  828.89   145.4  829.33   155.1  829.87
   164.8  830.13   174.5  830.27   184.2  830.69   193.9  831.78   203.6  834.24
   213.2  838.09   222.9  842.42   231.9  846.19   249.9  853.32   258.9  857.07
   267.8  860.93   285.8   868.9   294.8  873.09   312.8  881.94
#Mann= 3 , 0 , 0
       0      .1       0   120.2    .045       0   135.2      .1       0
Bank Sta=120.2,135.2
XS Rating Curve= 0 ,0
Exp/Cntr=0.3,0.1

Type RM Length L Ch R = 1 ,1274.4  ,99.2,93.7,85.8
XS GIS Cut Line= 3
     1571695.387      286974.155     1571629.365      287001.106
     1571442.124      287055.542
#Sta/Elev= 24
       0  873.44    17.8  866.97    26.7   863.2    35.7  858.52    44.6  853.07
    53.5  847.27    62.4  841.67    71.3  836.31    81.1   831.4    90.8  829.04
   100.6   828.2   110.3  827.14   120.1  826.73   129.8  827.67   139.6  828.92
   149.3  829.84   168.8  831.29   178.6  832.94   188.3  836.31   198.1   840.9
   217.6  850.99     237  861.15   246.8  866.16   266.3  875.88
#Mann= 3 , 0 , 0
       0      .1       0   110.3    .045       0   129.8      .1       0
Bank Sta=110.3,129.8
XS Rating Curve= 0 ,0
Exp/Cntr=0.3,0.1

Type RM Length L Ch R = 1 ,1180.8  ,145.1,144.2,143.3
XS GIS Cut Line= 2
     1571644.556      286874.586     1571445.988      287017.816
#Sta/Elev= 28
       0  873.18     9.8  869.82    19.6  866.37    29.4  862.54    39.2  857.09
      49  850.36    58.8  842.89    68.6   834.5    78.4  826.96    87.6  823.96
    88.1   823.8    97.9  824.24   102.6  824.56   107.7   824.9   117.5  825.43
   127.3  825.94   137.1  826.55   146.9   827.2   156.7  827.94   166.5  829.03
   176.3  831.15   186.1  835.03   195.9  840.05   205.7  845.15   215.4  850.24
   225.2  855.32     235  860.35   244.8  865.35
#Mann= 3 , 0 , 0
       0      .1       0    87.6    .045       0   102.6      .1       0
Bank Sta=87.6,102.6
XS Rating Curve= 0 ,0
Exp/Cntr=0.3,0.1

Type RM Length L Ch R = 1 ,1036.6  ,178.3,179.4,180.1
XS GIS Cut Line= 3
     1571581.622      286741.557      1571417.56      286866.557
     1571339.843      286907.997
#Sta/Elev= 29
       0  890.16     9.8   885.6    19.6  880.81    29.5  875.54    39.3  869.76
    49.1   863.3    58.9  855.97    68.8  847.61    78.6  838.07    88.4  829.47
    98.2  824.16   106.5  822.64     108  822.37   117.9  822.02   121.5  822.21
   127.7  822.54   157.2  824.69     167  825.63   176.8  826.85   186.6  828.52
   196.4     831   206.3  834.62   225.8  842.53   235.6  846.66   245.4  851.07
   255.2  855.83     265  861.05   274.8  866.86   294.3     880
#Mann= 3 , 0 , 0
       0      .1       0   106.5    .045       0   121.5      .1       0
Bank Sta=106.5,121.5
XS Rating Curve= 0 ,0
Exp/Cntr=0.3,0.1

Type RM Length L Ch R = 1 ,857.1   ,197.5,195.7,193.4
XS GIS Cut Line= 2
     1571504.902      286606.006     1571238.296      286771.155
#Sta/Elev= 26
       0     870     9.8  864.77    19.6  859.38    29.4  853.87    39.2  848.23
      49  842.44    58.8  836.78    68.6  831.36    78.4  826.73    88.2   823.7
      98  822.12   107.8  821.36   108.9  821.34   117.6  821.18   123.9  821.36
   127.4  821.46   137.2  822.03   176.4  824.82     196  826.08   205.8  827.29
   215.6   830.4   225.4  834.81   284.2  864.44     294  869.49   303.8  874.66
   313.6     880
#Mann= 3 , 0 , 0
       0      .1       0   108.9    .045       0   123.9      .1       0
Bank Sta=108.9,123.9
XS Rating Curve= 0 ,0
Exp/Cntr=0.3,0.1

Type RM Length L Ch R = 1 ,661.4   ,103.9,115.6,127.6
XS GIS Cut Line= 4
     1571404.756       286460.09     1571332.704       286495.41
     1571210.528      286596.809     1571138.129      286643.633
#Sta/Elev= 24
       0  856.91    17.8  848.11    35.7  839.47    53.5     831    62.4  827.11
    71.3  824.46    80.2  823.12    89.6  822.61    98.9  822.29   117.6  821.88
     155  821.48   164.3  821.11   173.6  820.11   178.2   819.7     183  819.27
   192.3  819.74   193.2  819.94     211  823.84   220.3  826.19   229.7  830.09
     239  835.64   277.3  860.16   296.5   872.2   325.2  889.98
#Mann= 3 , 0 , 0
       0      .1       0   178.2    .045       0   193.2      .1       0
Bank Sta=178.2,193.2
XS Rating Curve= 0 ,0
Exp/Cntr=0.3,0.1

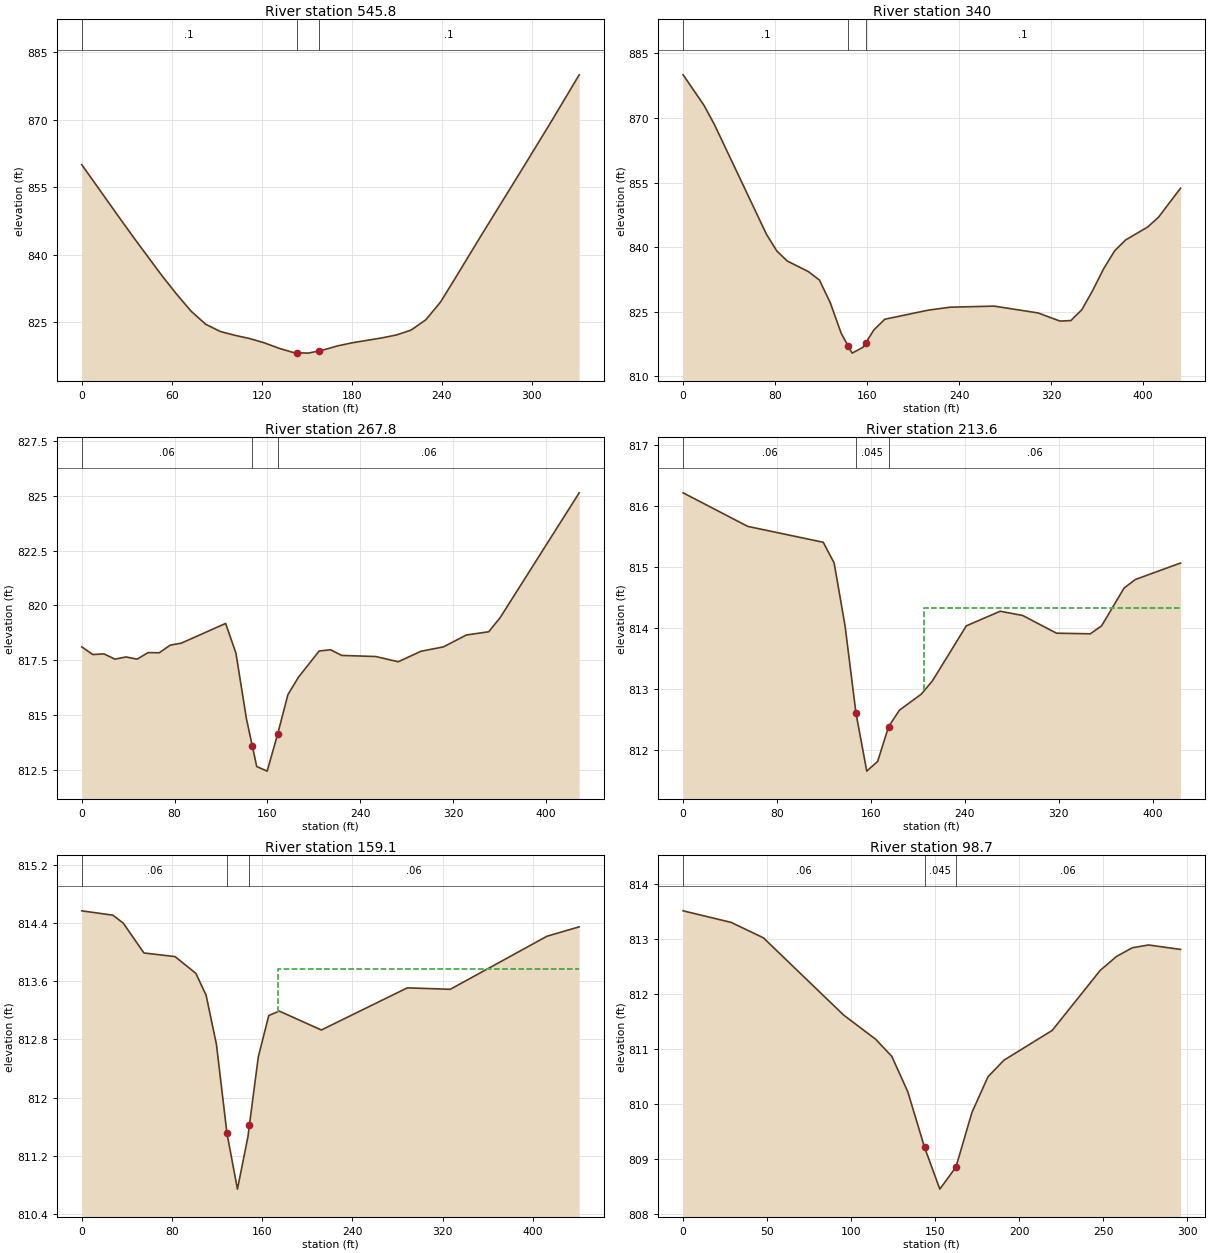
Type RM Length L Ch R = 1 ,545.8   ,208.7,205.9,201.1
XS GIS Cut Line= 4
     1571389.713      286419.001     1571339.652      286437.304
     1571156.275      286467.685     1571070.975      286503.482
#Sta/Elev= 29
       0     860    26.6   847.5    35.5  843.39    53.3  835.37    63.1  831.25
    72.9   827.4    82.6   824.5    92.4  822.88   102.2  822.03     112  821.31
   121.8  820.35   131.6  819.14   141.4  818.18   143.2  818.16   151.1  818.07
   158.2  818.57   160.9  818.76   170.7  819.69   180.5  820.38     200  821.45
   209.8  822.11   219.6   823.2   229.4  825.48   239.2  829.43   248.4   834.4
   266.9  844.55   294.7  859.57   313.2  869.67   331.7     880
#Mann= 3 , 0 , 0
       0      .1       0   143.2    .045       0   158.2      .1       0
Bank Sta=143.2,158.2
XS Rating Curve= 0 ,0
Exp/Cntr=0.3,0.1

Type RM Length L Ch R = 1 ,340     ,72.1,72.1,73.2
XS GIS Cut Line= 4
     1571377.695      286269.758     1571285.398      286232.225
     1571186.925      286266.219     1570965.303      286323.371
#Sta/Elev= 30
       0     880    18.1  872.95    27.2  868.47    72.5     843    81.5  839.12
    90.6  836.79   109.1  834.32   118.6  832.37     128  827.11   137.5  820.03
   143.8  816.97     147  815.42   156.5  816.78   158.8  817.76   165.9   820.8
   175.4  823.28   213.4   825.4   232.4  826.08   270.6  826.33   308.7  824.75
   327.8  822.86   337.3  822.97   346.9  825.51   356.4  830.03   365.9  835.05
   375.5   839.2     385   841.7   404.1  844.68   413.6  846.98   432.7  853.69
#Mann= 3 , 0 , 0
       0      .1       0   143.8    .045       0   158.8      .1       0
Bank Sta=143.8,158.8
XS Rating Curve= 0 ,0
Exp/Cntr=0.3,0.1

Type RM Length L Ch R = 1 ,267.8   ,52.7,54.2,54.8
XS GIS Cut Line= 4
     1571353.758      286108.527     1571246.336      286170.376
     1571170.381      286197.503     1570952.282      286249.586
#Sta/Elev= 30
       0  818.11     9.5  817.76    19.1  817.79    28.6  817.55    38.1  817.65
    47.7  817.55    57.2  817.85    66.7  817.84    76.3  818.19    85.8  818.28
     124  819.18   132.9  817.82   141.9  814.84     147  813.59   150.8  812.65
   159.8  812.44   168.8  814.12   177.7  815.93   186.7  816.72   204.6  817.92
   214.4  817.98   224.1  817.72   253.4  817.67   272.8  817.43   292.4  817.91
   311.8  818.11   331.4  818.65   350.8   818.8   360.6  819.44   428.8  825.14
#Mann= 3 , 0 , 0
       0     .06       0     147    .045       0   168.8     .06       0
Bank Sta=147,168.8
XS Rating Curve= 0 ,0
Exp/Cntr=0.3,0.1

Type RM Length L Ch R = 1 ,213.6   ,54.8,54.5,55.1
XS GIS Cut Line= 4
     1571356.905      286069.645     1571248.398      286119.558
     1571168.103      286142.345     1570951.197      286184.482
#Sta/Elev= 21
       0  816.21    55.1  815.66   119.4   815.4   128.7  815.06     138  814.03
   147.3   812.6   156.5  811.65   165.8  811.81   175.1  812.38   184.4  812.65
   202.9  812.91   212.5  813.13   241.3  814.03   270.2  814.27   289.4   814.2
   318.2  813.91     347   813.9   356.6  814.03   375.8  814.65   385.4  814.79
   423.9  815.06
#Mann= 3 , 0 , 0
       0     .06       0   147.3    .045       0   175.1     .06       0
#XS Ineff= 2 , 0
                          205.63          814.32
Permanent Ineff=
       F       F
Bank Sta=147.3,175.1
XS Rating Curve= 0 ,0
Exp/Cntr=0.3,0.1

Type RM Length L Ch R = 1 ,159.1   ,59.8,60.4,60.9
XS GIS Cut Line= 4
     1571332.058      286022.002     1571223.551      286071.915
     1571143.256      286094.701     1570912.134       286151.93
#Sta/Elev= 20
       0  814.57    27.6  814.51    36.8   814.4    55.1  813.99    82.7  813.94
   101.1  813.71   110.2  813.41   119.4  812.73   128.7  811.51     138  810.74
   147.3  811.46   148.6  811.62   156.5  812.56   165.8  813.13   175.1  813.19
   212.4  812.93   288.6  813.51   326.7  813.49   412.4  814.22     441  814.35
#Mann= 3 , 0 , 0
       0     .06       0   128.7    .045       0   148.6     .06       0
#XS Ineff= 2 , 0
                          173.94          813.77
Permanent Ineff=
       F       F
Bank Sta=128.7,148.6
XS Rating Curve= 0 ,0
Exp/Cntr=0.3,0.1

Type RM Length L Ch R = 1 ,98.7    ,49.9,53,56.3
XS GIS Cut Line= 2
     1571323.378      285985.109     1571036.919      286059.979
#Sta/Elev= 19
       0  813.51    28.6   813.3    47.8  813.02    95.5  811.62   114.6  811.18
   124.2  810.87   133.7  810.23   143.7  809.22   152.8  808.46   162.4  808.86
   171.9  809.85   181.5   810.5     191   810.8   219.7  811.34   248.3  812.43
   257.9  812.68   267.4  812.84     277  812.89   296.1  812.81
#Mann= 3 , 0 , 0
       0     .06       0   143.7    .045       0   162.4     .06       0
Bank Sta=143.7,162.4
XS Rating Curve= 0 ,0
Exp/Cntr=0.3,0.1

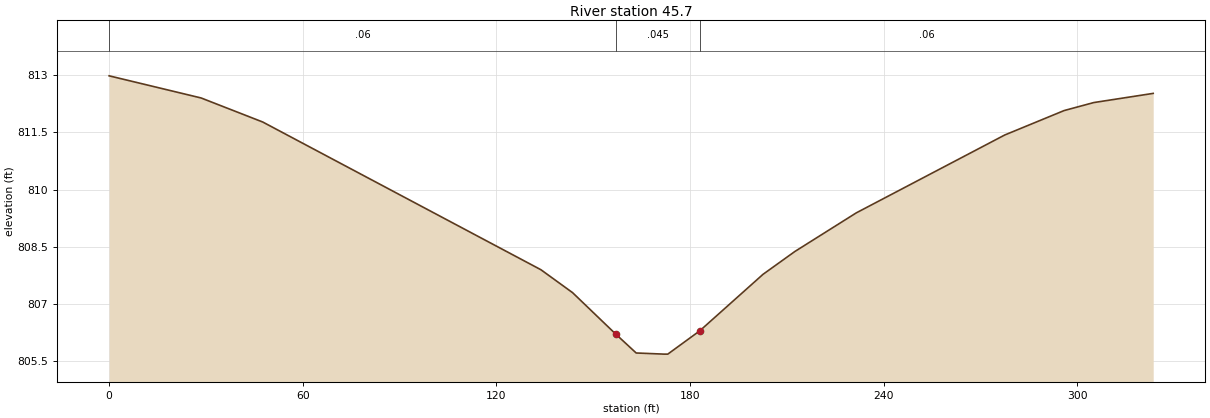
Type RM Length L Ch R = 1 ,45.7    ,46.2,45.7,44.3
XS GIS Cut Line= 4
      1571320.12      285975.064     1571206.188      285968.554
     1571098.766      285981.574     1571019.556      286044.508
#Sta/Elev= 17
       0  812.98    28.5   812.4    47.6  811.77   133.8   807.9   143.6   807.3
   156.9  806.22   163.3  805.72   171.9  805.69   173.1  805.69     183   806.3
   202.6  807.78   212.5  808.38   231.5  809.39   277.5  811.43   295.9  812.07
   305.1  812.28   323.5  812.52
#Mann= 3 , 0 , 0
       0     .06       0   156.9    .045       0     183     .06       0
Bank Sta=156.9,183
XS Rating Curve= 0 ,0
Exp/Cntr=0.3,0.1

Chan Stop Cuts=-1
Use User Specified Reach Order=0
Composite Channel Slope=5